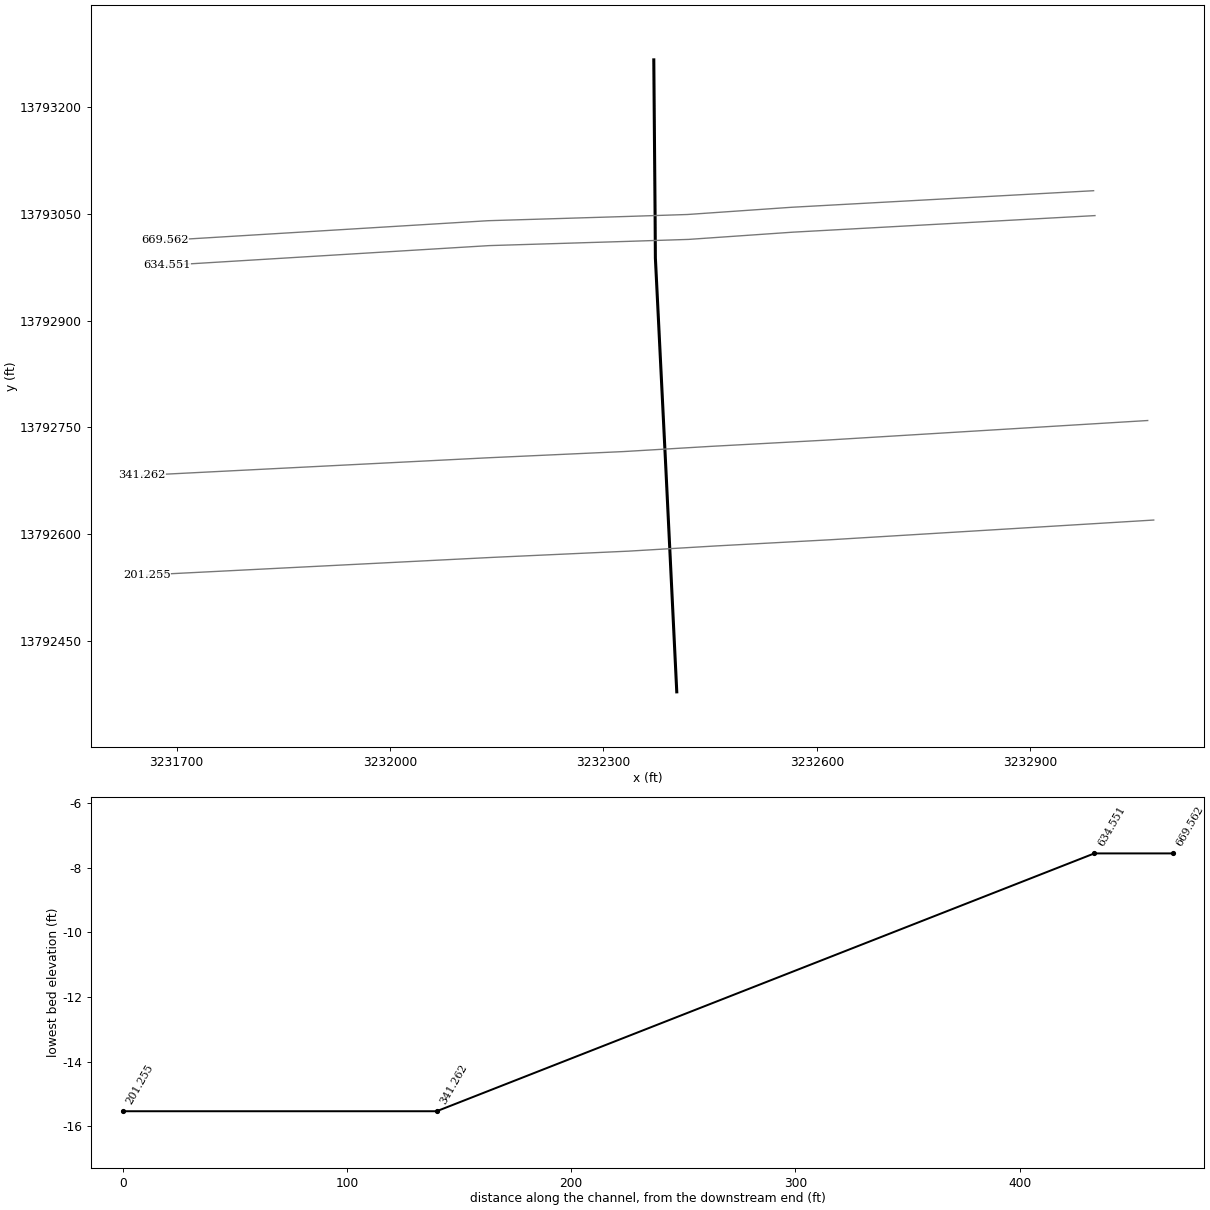
--- A104_14_00.prj (project) ---

Proj Title=A104-14-00
Current Plan=p01
Default Exp/Contr=.3,.1
English Units
Geom File=g01
Geom File=g02
Flow File=f01
Flow File=f02
Plan File=p01
Plan File=p02
Y Axis Title=Elevation
X Axis Title(PF)=Main Channel Distance
X Axis Title(XS)=Station
BEGIN DESCRIPTION:
Clear Creek Basin
Taylor Bayou Diversion Channel
A104-14-00
Flood Hazard Model
10, 2, 1 & 0.2% Events
Filename: A104_14_00.prj
Prepared by: Perry Vaught	Date: 4-30-04
Reviewed by: __________	Date:
Status (FINAL)
END DESCRIPTION:
DSS Export Rating Curves= 0
DSS Export Rating Curve Sorted= 0
DSS Export Volume Flow Curves= 0
DXF OffsetX= 0
DXF OffsetY= 0
DXF ScaleX= 1
DXF ScaleY= 10

--- A104_14_00.p01 (plan) ---

Plan Title=FEMA Effective June 2007
Version=Version 3.0.1  Mar 2001
Short Identifier=FEMAeff0607
Geom File=g01
Flow File=f01
Subcritical Flow
K Sum by GR= 0
Std Step Tol= 0.003
Critical Tol= 0.003
Num of Std Step Trials= 20
Max Error Tol= 0.1
Flow Tol Ratio= 0.001
Split Flow NTrial= 30
Split Flow Tol= 0.02
Split Flow Ratio= 0.02
Log Output Level= 0
Friction Slope Method= 0
Unsteady Friction Slope Method= 2
Secant Critical Depth
Global Vel Dist= 0 , 0 , 0
Global Log Level= 0
CheckData=True
Encroach Param=-1 ,0,0, 0
Computation Interval=1HOUR
Output Interval=1HOUR
Run HTab= 0
Run UNet= 0
Run PostProcess= 0
UNET Theta= 1
UNET ZTol= 0.02
UNET ZSATol= 0.1
UNET MxIter= 20
UNET MaxInSteps= 20
UNET DtIC= 0
UNET DtMin= 0
UNET MaxCRTS= 20
UNET WFStab= 2
UNET SFStab= 1
UNET WFX= 1
UNET SFX= 1
UNET Convert EG Bridges=-1
UNET Use Existing IB Tables=-1
Instantaneous Interval=1HOUR
Write IC File= 0
IC Time=0
Write Velocity= 0
Write Detailed= 0

--- A104_14_00.p02 (plan) ---

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Plan Title=Floodway
Short Identifier=Floodway0607
Geom File=g02
Flow File=f02
Encroach Param=-1 ,0,0, 2
Encroach River=A104-14-00
Encroach Reach=A104-14-00_0002
Encroach Node=669.562
       1 4945.43  5054.5
Encroach Node=634.551
       1 4945.43  5054.5
Encroach Node=487.5
       1 4944.88  5059.5
Encroach Node=341.262
       1 4944.88  5059.5
Encroach Node=201.255
       1 4917.07 5100.85

--- A104_14_00.f01 (steady flow) ---

Flow Title=FEMA Effective June 2007
Version=Version 3.0.1  Mar 2001
Number of Profiles= 4
Profile Names=10PCT_10yr, 2PCT_50yr, 1PCT_100yr, 0.2PCT_500yr
River Rch & RM=A104-14-00,A104-14-00_0002      ,669.562
     837    1257    1475    2110
Boundary for River Rch & Prof#=A104-14-00,A104-14-00_0002      , 1
Up Type= 0
Dn Type= 1
Dn Known WS=.9
Boundary for River Rch & Prof#=A104-14-00,A104-14-00_0002      , 2
Up Type= 0
Dn Type= 1
Dn Known WS=1.3
Boundary for River Rch & Prof#=A104-14-00,A104-14-00_0002      , 3
Up Type= 0
Dn Type= 1
Dn Known WS=1.45
Boundary for River Rch & Prof#=A104-14-00,A104-14-00_0002      , 4
Up Type= 0
Dn Type= 1
Dn Known WS=1.75
DSS Import GetInterval= 0
DSS Import GetPeak= 0
DSS Import FillOption= 0

--- A104_14_00.f02 (steady flow) ---

Flow Title=Floodway
Version=Version 3.0.1  Mar 2001
Number of Profiles= 2
Profile Names=1PCT_100yr, 1PCTFloodway_100yrFW
River Rch & RM=A104-14-00,A104-14-00_0002      ,669.562
    1475    1475
Boundary for River Rch & Prof#=A104-14-00,A104-14-00_0002      , 1
Up Type= 0
Dn Type= 1
Dn Known WS=1.45
Boundary for River Rch & Prof#=A104-14-00,A104-14-00_0002      , 2
Up Type= 0
Dn Type= 1
Dn Known WS=2.45
DSS Import GetInterval= 0
DSS Import GetPeak= 0
DSS Import FillOption= 0

--- A104_14_00.g01 (geometry) ---

Geom Title=A104-14-00 June 2007
Version=Version 3.0.1  Mar 2001

River Reach=A104-14-00    ,A104-14-00_0002
Reach XY= 30
      3232370.75       13793266.       3232370.8    13793260.053
     3232371.317    13793198.256     3232371.385    13793190.215
     3232371.919    13793126.364      3232372.28    13793083.289
     3232372.421    13793066.364     3232372.593    13793045.906
     3232372.618    13793042.103     3232372.979    13792987.771
     3232373.473    13792977.856     3232375.628    13792934.628
     3232377.728    13792892.482     3232382.993    13792786.857
     3232383.266    13792781.364     3232384.296    13792760.694
     3232385.509    13792736.364     3232385.831    13792729.897
     3232387.471    13792696.993     3232387.553    13792695.354
     3232388.481    13792676.364     3232391.076    13792623.308
     3232391.797    13792608.558     3232393.761      13792568.4
     3232395.963    13792523.365     3232397.648     13792488.89
     3232398.946    13792462.351     3232400.614    13792428.234
     3232401.226    13792415.734     3232403.043    13792378.574

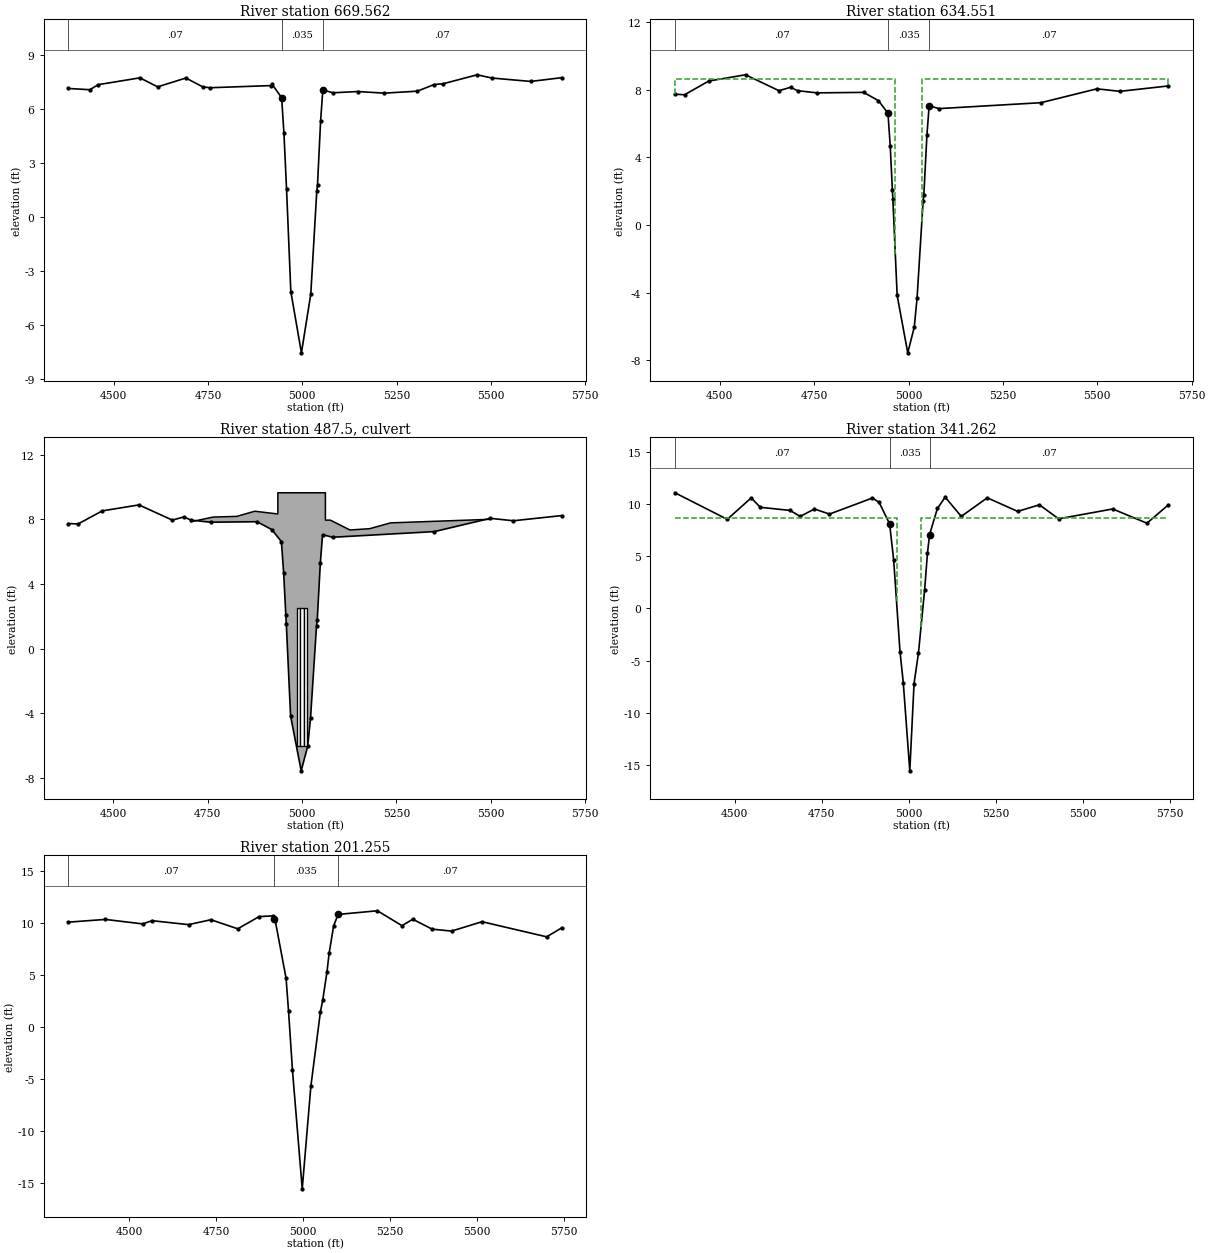
Type RM Length L Ch R = 1 ,669.562 ,35,35.01,35.02
XS GIS Cut Line= 6
     3232989.014    13793082.271     3232564.392    13793059.005
        3232418.    13793048.859      3232328.57    13793045.974
     3232137.686    13793040.145     3231683.721      13793012.5
#Sta/Elev= 30
 4380.36    7.13 4437.29    7.06 4459.13    7.34 4569.76    7.72 4616.79    7.22
 4691.65    7.71 4736.37    7.22 4754.97    7.17 4917.22    7.29 4920.18    7.36
 4945.43    6.62 4951.44    4.66 4958.46    1.52 4969.74   -4.15 4997.82   -7.55
  5022.6   -4.29 5038.51    1.43 5040.44    1.78 5048.56     5.3  5054.5    7.05
 5081.14    6.89 5147.26    6.96 5216.95    6.87 5304.92    6.98 5349.79    7.35
 5373.04    7.39 5463.39    7.89 5502.31    7.71 5605.42    7.52 5687.62    7.73
#Mann= 3 ,-1 , 0
 4380.36     .07       0 4945.43    .035       0  5054.5     .07       0
Bank Sta=4945.43,5054.5
XS Rating Curve= 0
Exp/Cntr=.5,.3

Type RM Length L Ch R = 1 ,634.551 ,294.26,293.29,295.83
XS GIS Cut Line= 6
     3232990.929    13793047.324      3232566.56    13793024.071
     3232419.774    13793013.898     3232329.669    13793010.991
     3232139.284    13793005.178     3231685.848    13792977.565
#Sta/Elev= 27
 4381.11    7.74 4406.67    7.71 4470.69    8.52 4568.07    8.89  4656.6    7.95
 4687.37    8.15 4705.76    7.95 4757.64    7.82 4880.93    7.85 4920.18    7.36
 4945.43    6.62 4951.44    4.66 4957.08    2.08 4958.46    1.52 4969.74   -4.15
 4997.82   -7.55  5015.1   -6.03  5022.6   -4.29 5038.51    1.43 5040.44    1.78
 5048.56     5.3  5054.5    7.05 5081.14    6.89 5350.74    7.24 5499.07    8.06
 5559.81    7.91 5688.16    8.23
#Mann= 3 ,-1 , 0
 4381.11     .07       0 4945.43    .035       0  5054.5     .07       0
#XS Ineff= 2 , 0
       0    4965    8.63    5035       0    8.63
Permanent Ineff=
       F       F
Bank Sta=4945.43,5054.5
XS Rating Curve= 0
Exp/Cntr=.5,.3

Type RM Length L Ch R = 2 ,487.5   ,,,
BEGIN DESCRIPTION:
Diversion Structure
END DESCRIPTION:
Bridge Culvert--1,0,-1,-1, 0
Deck Dist Width WeirC Skew NumUp NumDn MinLoCord MaxHiCord MaxSubmerge Is_Ogee
37,218,2.6,0, 14, 4, , , .95, 0, 0,0,,
    4706    4765    4827    4875    4932    4936    4936    5062    5062    5075
    5127    5179    5235    5499
    7.85    8.14    8.18     8.5    8.34    8.34    9.64    9.64    7.95    7.95
    7.34    7.42    7.78       8
                                                                                
                                
    4935    5063    5063    5100
    9.68    9.68    7.95    7.95
                                
Multiple Barrel Culv=2,8.5,9,255,.015,.5,1,8,2,-6,-6.2, 3,Culvert #1  , 0 ,22
    4990    4990    5000    5000    5010    5010
Culvert Bottom n=.015
BC Design=,, 0 ,, 0 ,,,,,,

Type RM Length L Ch R = 1 ,341.262 ,141.99,140.01,143.62
XS GIS Cut Line= 6
     3233065.048    13792759.567     3232611.612    13792731.954
     3232450.294    13792723.234     3232328.215    13792715.967
     3232137.831    13792707.247     3231650.969    13792682.541
#Sta/Elev= 30
 4328.72   11.06 4478.85    8.52 4547.56   10.57 4573.72    9.67 4659.41    9.37
 4688.11     8.8 4729.16    9.51 4772.12    9.02 4895.69   10.56 4914.83   10.14
 4944.88    8.08 4956.44    4.66 4974.74   -4.15  4984.1    -7.1 5002.82  -15.54
    5015    -7.2  5027.6   -4.29 5045.44    1.78 5053.56     5.3  5059.5    7.05
    5082    9.56 5104.41   10.64 5150.57     8.8 5225.18   10.58 5312.43    9.28
 5374.95    9.91 5429.94    8.57 5585.29    9.51 5683.59    8.15 5744.92     9.9
#Mann= 3 ,-1 , 0
 4328.72     .07       0 4944.88    .035       0  5059.5     .07       0
#XS Ineff= 2 , 0
       0    4965    8.68    5035       0    8.68
Permanent Ineff=
       F       F
Bank Sta=4944.88,5059.5
XS Rating Curve= 0
Exp/Cntr=.5,.3

Type RM Length L Ch R = 1 ,201.255 ,166.5,201.26,144.52
XS GIS Cut Line= 6
     3233073.558    13792619.826     3232619.646    13792592.184
     3232458.232    13792583.459     3232335.578    13792576.158
     3232144.581     13792567.41     3231658.064    13792542.721
#Sta/Elev= 30
 4325.93   10.06 4432.22   10.32 4539.47    9.89 4566.21    10.2 4671.19    9.82
 4735.41   10.29 4812.53    9.42 4873.92   10.59 4912.41   10.66 4917.07   10.37
 4920.57   10.15 4951.44    4.66 4958.46    1.52 4969.74   -4.15 4997.82  -15.54
  5022.6    -5.7    5050    1.43    5057    2.63    5069     5.3    5075    7.05
    5088    9.69 5100.85    10.8 5213.86   11.15 5284.45    9.72 5315.53   10.34
 5370.74    9.39 5426.88     9.2 5514.53    10.1 5700.16    8.65 5743.54    9.51
#Mann= 3 ,-1 , 0
 4325.93     .07       0 4917.07    .035       0 5100.85     .07       0
Bank Sta=4917.07,5100.85
XS Rating Curve= 0
Exp/Cntr=.3,.1

Chan Stop Cuts=-1

--- A104_14_00.g02 (geometry) ---

Geom Title=A104-14-00 June 2007 (Floodway)
Version=Version 3.0.1  Mar 2001

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
River Reach=A104-14-00    ,A104-14-00_0002